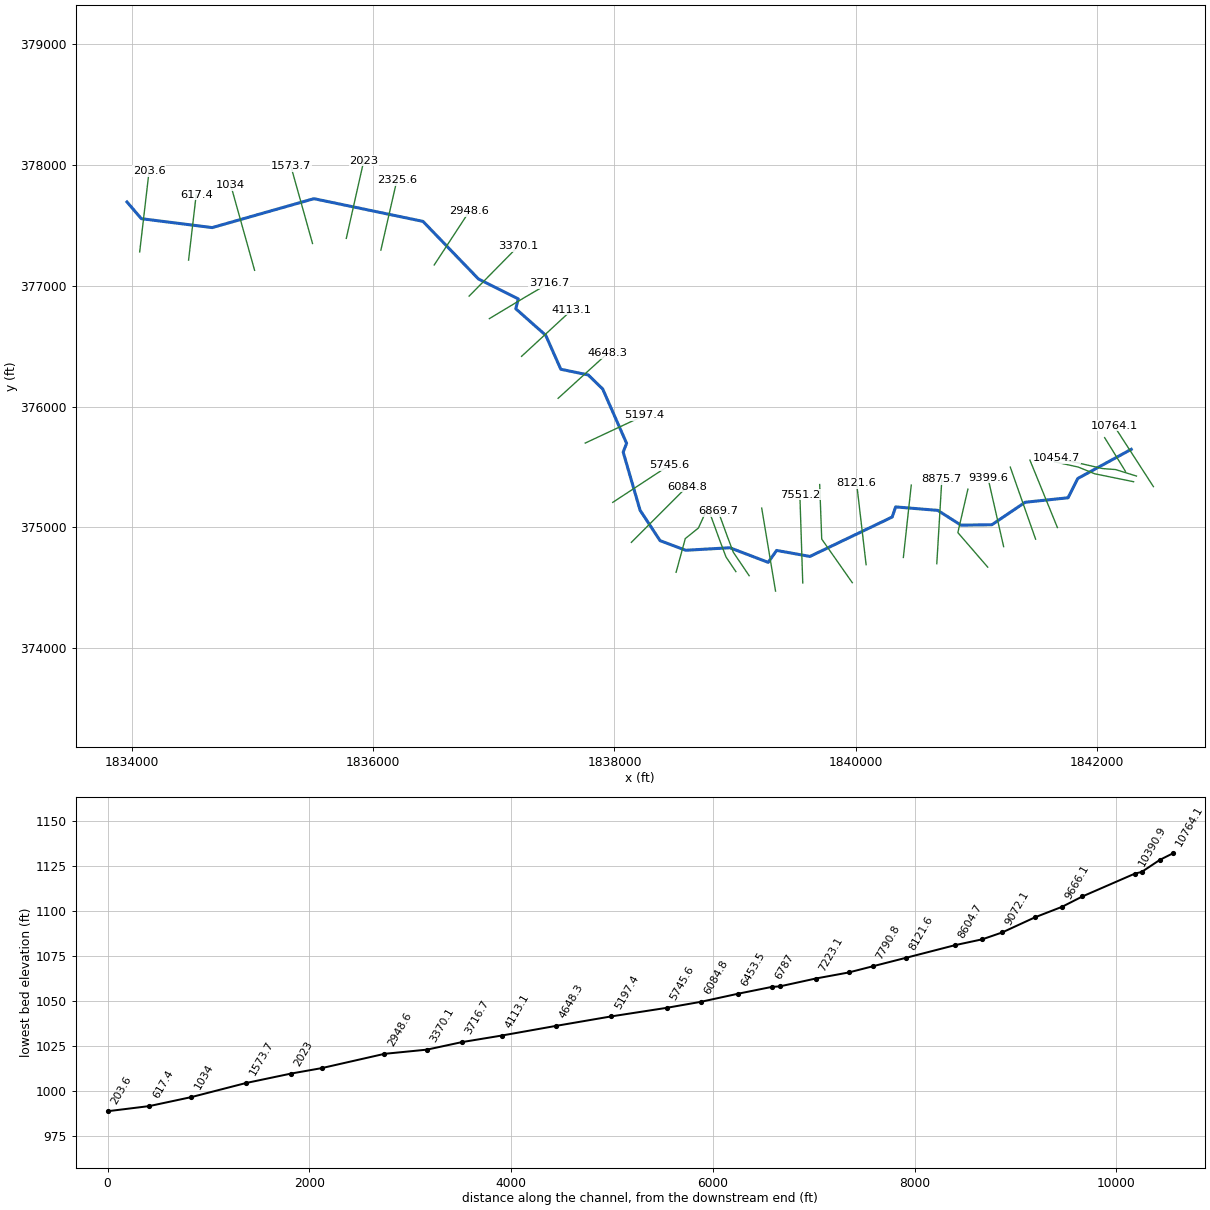
--- OwlCk.prj (project) ---

Proj Title=OwlCk
Current Plan=p01
Default Exp/Contr=0,0
English Units
Geom File=g01
Flow File=f01
Plan File=p01
BEGIN DESCRIPTION:
END DESCRIPTION:
DSS Export Rating Curves= 0
DSS Export Rating Curve Sorted= 0
DSS Export Volume Flow Curves= 0
DXF OffsetX= 0
DXF OffsetY= 0
DXF ScaleX= 0
DXF ScaleY= 0

--- OwlCk.p01 (plan) ---

Plan Title=Floodplain
Program Version=4.00
Geom File=g01
Flow File=f01
K Sum by GR=0
Std Step Tol=0.01
Critical Tol=0.01
Num of Std Step Trials=20
Max Error Tol=0.3
Flow Tol Ratio=0.001
Split Flow NTrial=30
Split Flow Tol=0.02
Split Flow Ratio=0.02
Log Output Level=0
Friction Slope Method=1
Unsteady Friction Slope Method=2
Unsteady Bridges Friction Slope Method=1
Global Log Level=0
CheckData=False
Run HTab=0
Run UNet=0
Run PostProcess=0
UNET Theta=0
UNET Theta Warmup=0
UNET ZTol=0
UNET ZSATol=0
UNET MxIter=0
UNET MaxInSteps=0
UNET DtIC=0
UNET DtMin=0
UNET MaxCRTS=0
UNET WFStab=0
UNET SFStab=0
UNET WFX=0
UNET SFX=0
UNET DSS MLevel=0
UNET DZMax Abort=0
UNET Convert EG Bridges=0
UNET Use Existing IB Tables=0
UNET Froude Limit=0
UNET Froude Power=0
Write IC File=0
Echo Input=False
Echo Output=False
Write Detailed=0

--- OwlCk.f01 (steady flow) ---

Flow Title=NFF Regression Equation
Program Version=4.00
Number of Profiles=1
Profile Names=P100yr
River Rch & RM=OwlCk,Main      ,10764.1
     718
River Rch & RM=OwlCk,Main      ,8875.7
    1136
River Rch & RM=OwlCk,Main      ,7223.1
    1207
River Rch & RM=OwlCk,Main      ,2948.6
    1294
River Rch & RM=OwlCk,Main      ,2325.6
    1527
River Rch & RM=OwlCk,Main      ,1573.7
    1550
River Rch & RM=OwlCk,Main      ,203.6
    1569
Boundary for River Rch & Prof#=OwlCk,Main      ,1
Up Type=0
Dn Type=3
Dn Slope=0.011392

--- OwlCk.g01 (geometry) ---

Geom Title=USGS 10m DEM
Program Version=4.10

River Reach=OwlCk           ,Main
Reach XY= 30
      1842285.29      375645.412     1841841.727      375403.546
     1841761.204      375243.877       1841405.2      375206.685
     1841129.921      375020.516     1840873.414      375016.932
      1840681.17      375139.418     1840331.266      375168.238
     1840303.026      375084.546     1839620.651      374757.812
     1839344.369      374807.592     1839274.873      374708.686
     1838956.934      374829.862     1838590.655      374808.902
     1838377.909      374888.813     1838212.062       375140.99
     1838072.113      375622.078     1838100.346      375694.995
     1837902.148      376145.342     1837782.356      376261.661
     1837554.752      376308.884     1837429.752      376590.134
     1837181.315      376810.273     1837202.148       376891.87
     1836871.593      377057.147     1836411.784      377534.057
     1835507.134      377722.167     1834663.944      377482.518
     1834076.118      377556.425     1833957.252      377694.853

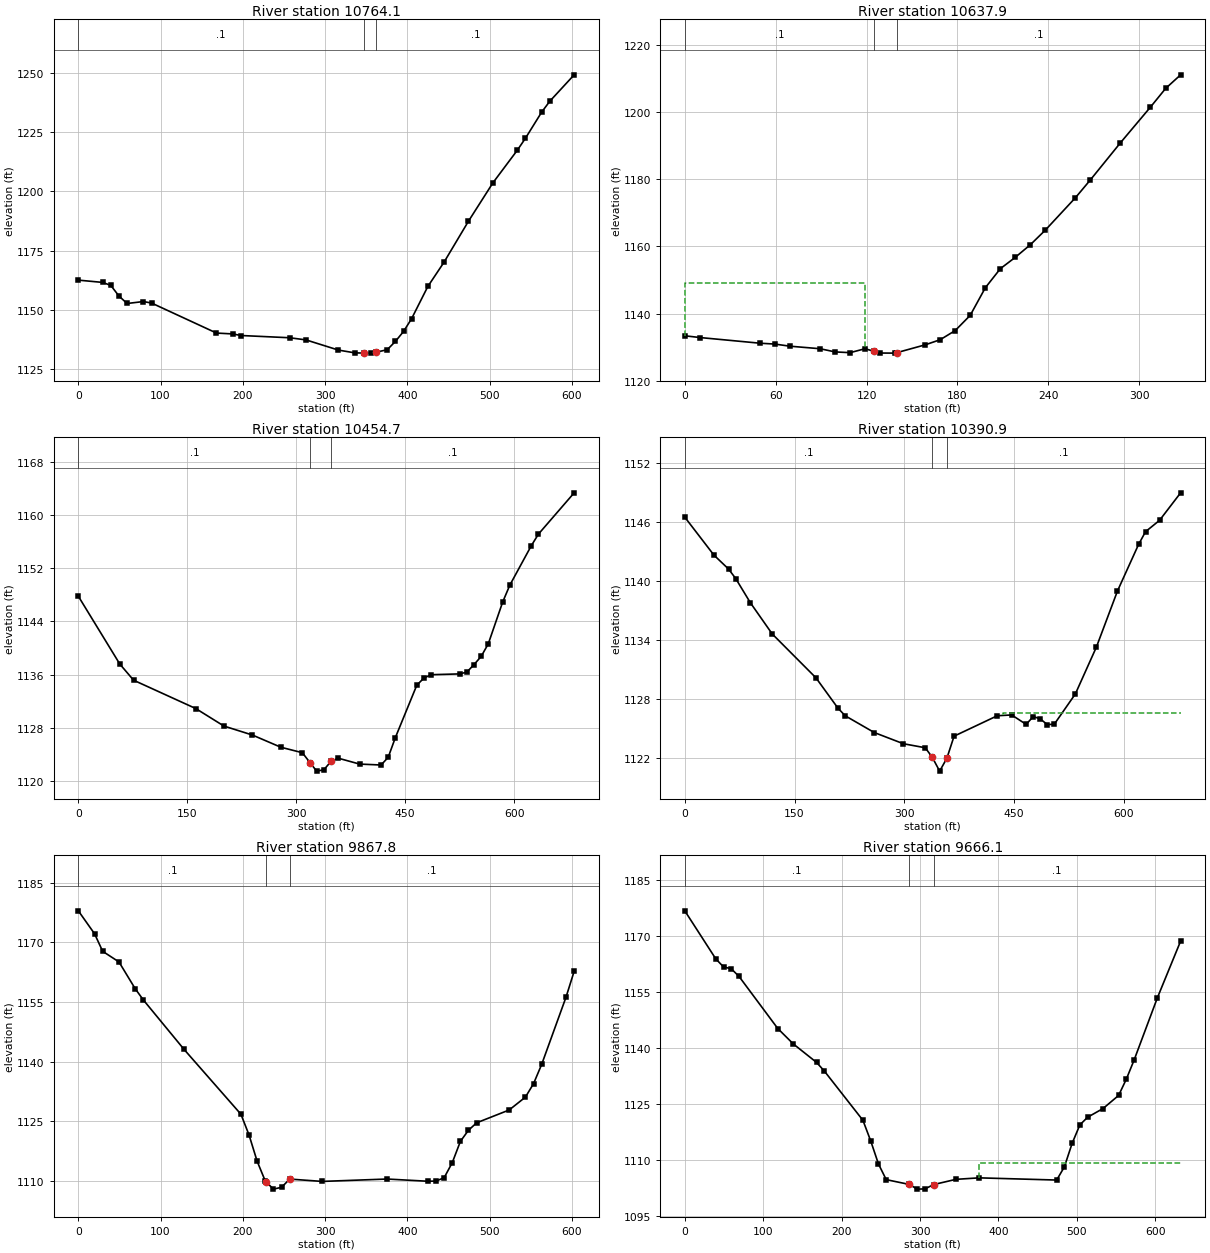
Type RM Length L Ch R = 1 ,10764.1 ,126.4,126.2,125.7
XS GIS Cut Line= 2
     1842469.074      375336.373     1842141.474      375842.541
#Sta/Elev= 30
       0 1162.55    29.6 1161.59    39.5 1160.32    49.4 1155.84    59.3  1152.7
    79.1 1153.52      89  1152.9     168 1140.24   187.8 1139.87   197.7 1139.21
     257 1138.26   276.8 1137.36   316.3 1133.06   336.1  1131.9   347.4 1131.79
   355.8 1131.78   362.4 1132.19   375.6 1133.22   385.5  1136.7   395.4  1140.9
   405.2 1146.27     425 1159.89   444.8 1170.18   474.4  1187.4   504.1 1203.56
   533.7 1217.27   543.6 1222.32   563.4 1233.37   573.3 1237.97   602.9 1249.09
#Mann= 3 , 0 , 0
       0      .1       0   347.4    .045       0   362.4      .1       0
Bank Sta=347.4,362.4
XS Rating Curve= 0 ,0
Exp/Cntr=0.3,0.1

Type RM Length L Ch R = 1 ,10637.9 ,153,183.2,203.7
XS GIS Cut Line= 2
     1842236.869      375463.543     1842064.925      375742.026
#Sta/Elev= 28
       0 1133.42     9.9  1132.9    49.6 1131.21    59.5 1130.95    69.4 1130.32
    89.3 1129.57    99.2 1128.62   109.1  1128.4     119 1129.57   125.1 1128.78
   128.9 1128.29   138.8 1128.26   140.1 1128.42   158.7 1130.73   168.6 1132.25
   178.5 1134.97   188.4 1139.49   198.4 1147.71   208.3 1153.37   218.2 1156.76
   228.1 1160.49     238 1164.84   257.9 1174.49   267.8 1179.81   287.6 1190.82
   307.4 1201.42   317.4 1206.96   327.3 1211.01
#Mann= 3 , 0 , 0
       0      .1       0   125.1    .045       0   140.1      .1       0
#XS Ineff= 2 , 0
          118.94 1149.03
Permanent Ineff=
       F       F
Bank Sta=125.1,140.1
XS Rating Curve= 0 ,0
Exp/Cntr=0.3,0.1

Type RM Length L Ch R = 1 ,10454.7 ,77.8,63.8,57.1
XS GIS Cut Line= 4
     1842328.443      375423.916     1842155.857      375477.577
     1842048.167      375485.962     1841664.306      375574.018
#Sta/Elev= 30
       0 1147.77    57.1 1137.57    76.1 1135.14   161.7 1130.88   200.4 1128.25
   239.6  1126.9   278.9 1125.06   308.4 1124.24   319.2 1122.71   328.1 1121.47
     338 1121.67   347.8 1122.93   357.7 1123.42   387.2 1122.53   416.8 1122.39
   426.6 1123.55   436.4  1126.5     466  1134.4   475.8 1135.47   485.7 1135.97
     525 1136.09   534.9 1136.36   544.7 1137.49   554.6 1138.72   564.4 1140.62
   584.1 1146.87     594 1149.43   623.5 1155.35   633.4 1157.11   682.6 1163.32
#Mann= 3 , 0 , 0
       0      .1       0   319.2    .045       0   347.8      .1       0
Bank Sta=319.2,347.8
XS Rating Curve= 0 ,0
Exp/Cntr=0.3,0.1

Type RM Length L Ch R = 1 ,10390.9 ,543.2,523.1,504.7
XS GIS Cut Line= 4
     1842304.659      375377.041      1841982.54      375442.643
     1841845.823      375498.446     1841649.119      375541.693
#Sta/Elev= 30
       0  1146.5    39.8 1142.64    59.8 1141.22    69.7 1140.24    89.6 1137.79
   119.5 1134.61   179.3 1130.14   209.2 1127.07   219.2 1126.28     259 1124.57
   298.8 1123.43   328.7 1123.02   338.2 1122.06   348.4 1120.64   358.3 1121.96
   368.1  1124.2   427.2 1126.28   446.9 1126.36   466.6  1125.4   476.4  1126.2
     486 1125.96   495.6 1125.37   505.2 1125.43   533.9  1128.5   562.7 1133.28
   591.5 1138.99   620.3 1143.72   629.8 1145.02     649 1146.18   677.8 1148.98
#Mann= 3 , 0 , 0
       0      .1       0   338.2    .045       0   358.3      .1       0
#XS Ineff= 2 , 0
                          435.52         1126.61
Permanent Ineff=
       F       F
Bank Sta=338.2,358.3
XS Rating Curve= 0 ,0
Exp/Cntr=0.3,0.1

Type RM Length L Ch R = 1 ,9867.8  ,203.2,201.7,198.9
XS GIS Cut Line= 2
     1841672.994      374997.264     1841445.313      375555.555
#Sta/Elev= 30
       0 1177.96    19.8 1172.16    29.6 1167.77    49.4  1165.1    69.2 1158.34
    79.1 1155.52   128.5  1143.1   197.7 1126.77   207.6 1121.53   217.4 1114.95
   227.3 1109.96   228.7 1109.67   237.2 1107.92   247.1 1108.38     257 1110.45
   296.5 1109.86   375.6 1110.46     425  1109.9   434.9 1109.95   444.8 1110.79
   454.7 1114.59   464.6 1119.95   474.4 1122.74   484.3 1124.61   523.9 1127.84
   543.6 1131.07   553.5 1134.45   563.4 1139.31     593 1156.23   602.9 1162.75
#Mann= 3 , 0 , 0
       0      .1       0   228.7    .045       0     257      .1       0
Bank Sta=228.7,257
XS Rating Curve= 0 ,0
Exp/Cntr=0.3,0.1

Type RM Length L Ch R = 1 ,9666.1  ,269.1,266.5,262.9
XS GIS Cut Line= 2
     1841492.122      374901.142     1841282.295       375497.66
#Sta/Elev= 30
       0 1176.71    39.5 1163.85    49.4 1161.69    59.3 1161.19    69.2 1159.13
   118.6 1145.19   138.3 1141.08     168 1136.12   177.8 1133.85   227.2 1120.61
   237.1  1115.1     247 1108.92   256.9 1104.72   286.5 1103.43   296.4 1102.18
   306.3 1102.24   317.4  1103.4   345.8  1104.8   375.5  1105.2   474.3 1104.61
   484.1 1108.13     494 1114.43   503.9 1119.39   513.8 1121.44   533.5 1123.77
   553.3 1127.27   563.2 1131.66   573.1 1136.77   602.7 1153.39   632.4 1168.61
#Mann= 3 , 0 , 0
       0      .1       0   286.5    .045       0   317.4      .1       0
#XS Ineff= 2 , 0
                          375.11         1109.18
Permanent Ineff=
       F       F
Bank Sta=286.5,317.4
XS Rating Curve= 0 ,0
Exp/Cntr=0.3,0.1

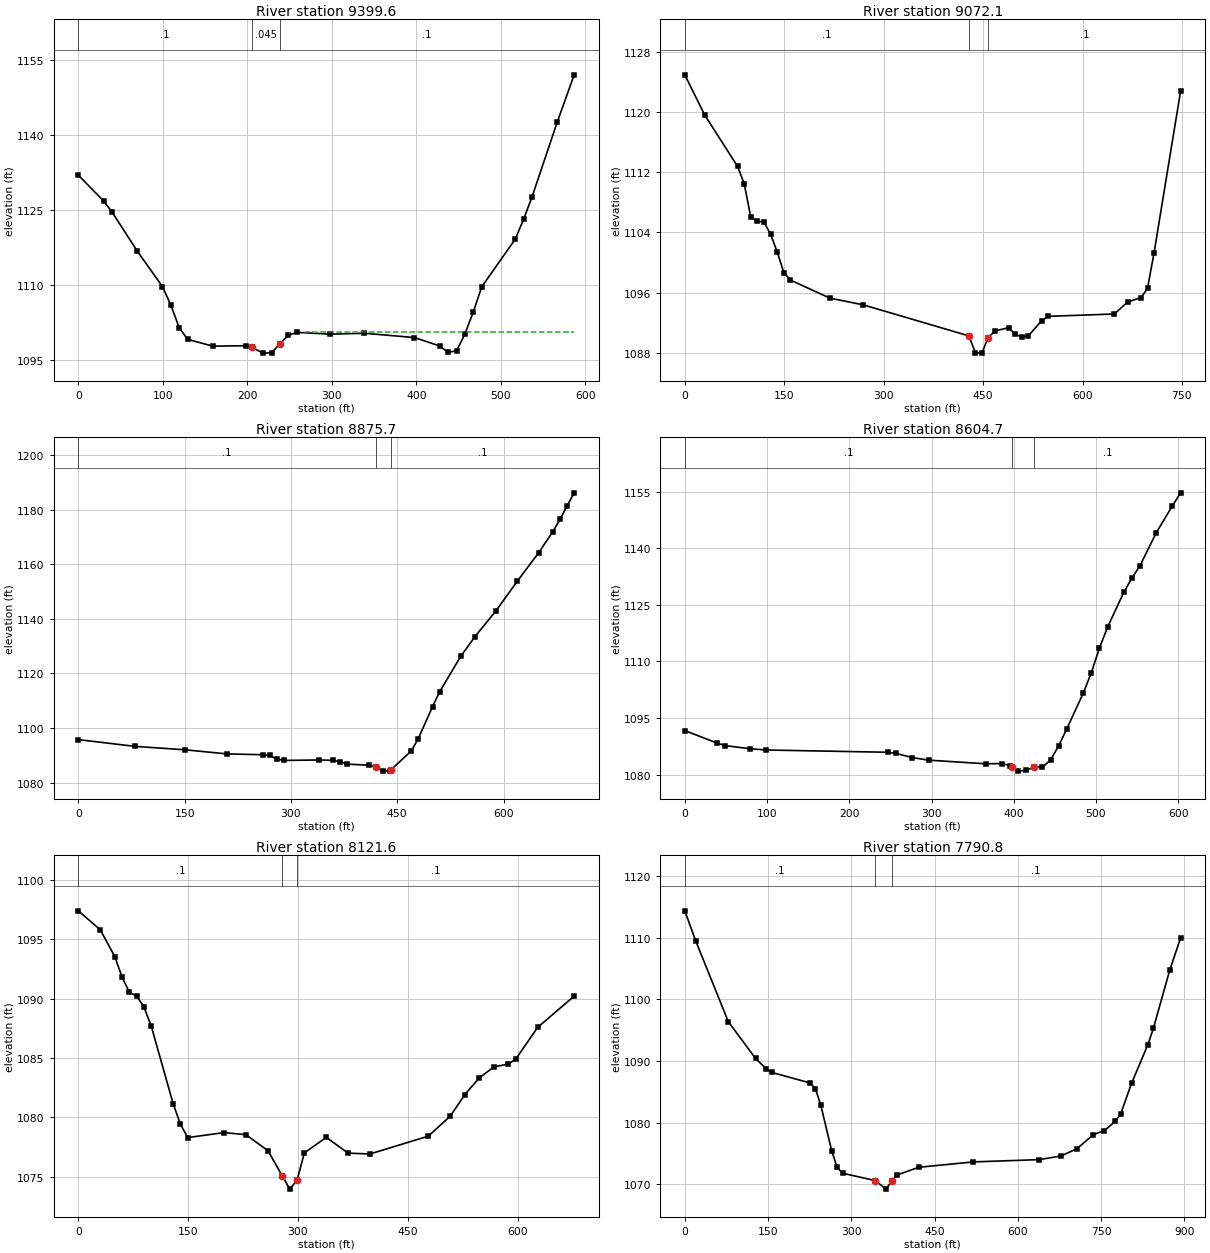
Type RM Length L Ch R = 1 ,9399.6  ,337.5,327.5,317.7
XS GIS Cut Line= 2
     1841227.094        374839.1     1841096.648      375411.226
#Sta/Elev= 30
       0 1132.02    29.8 1126.88    39.8 1124.67    69.6 1116.86    99.5 1109.73
   109.4 1106.06   119.4 1101.48   129.3 1099.16   159.1  1097.8   198.9 1097.88
   205.3 1097.54   218.8  1096.4   228.8 1096.46   238.7 1098.32   248.6 1099.97
   258.6 1100.56   298.4  1100.2   338.2 1100.38   397.8 1099.52   427.7 1097.83
   437.6 1096.57   447.6 1096.85   457.5 1100.23   467.5 1104.68   477.4 1109.66
   517.2 1119.25   527.1 1123.25   537.1 1127.75   566.9  1142.7   586.8 1152.11
#Mann= 3 , 0 , 0
       0      .1       0   205.3    .045       0   238.7      .1       0
#XS Ineff= 2 , 0
                          267.85         1100.54
Permanent Ineff=
       F       F
Bank Sta=205.3,238.7
XS Rating Curve= 0 ,0
Exp/Cntr=0.3,0.1

Type RM Length L Ch R = 1 ,9072.1  ,192.1,196.4,199.7
XS GIS Cut Line= 3
     1841095.136      374669.229     1840847.416      374955.453
      1840930.81      375315.377
#Sta/Elev= 30
       0 1124.94    29.9 1119.62    79.7 1112.76    89.6 1110.47    99.6 1106.01
   109.6  1105.5   119.5 1105.37   129.5 1103.74   139.5 1101.38   149.4 1098.67
   159.4 1097.66   219.2 1095.26     269 1094.38   428.5 1090.25   438.4 1088.02
   448.4 1087.96   457.3 1090.02   468.4 1090.91   488.4 1091.34   498.4 1090.46
   508.4 1090.12   518.3 1090.25   538.3 1092.27   548.3 1092.85   648.1 1093.16
   668.1 1094.76   688.1 1095.33   698.1 1096.57     708 1101.33     748  1122.8
#Mann= 3 , 0 , 0
       0      .1       0   428.5    .045       0   457.3      .1       0
Bank Sta=428.5,457.3
XS Rating Curve= 0 ,0
Exp/Cntr=0.3,0.1

Type RM Length L Ch R = 1 ,8875.7  ,274.2,271,268.6
XS GIS Cut Line= 2
     1840672.715      374697.617     1840714.605      375396.049
#Sta/Elev= 30
       0 1095.72      80 1093.25   149.9 1092.01   209.9 1090.49   259.9 1090.19
   269.9 1089.91   279.9 1088.64   289.9  1088.1   339.8 1088.27   359.8 1088.13
   369.8 1087.59   379.8 1086.74   409.8 1086.35   419.8 1085.86   429.8 1084.18
   439.8 1084.32   441.3  1084.7   469.8 1091.56   479.8 1096.11   499.8  1107.8
   509.8 1113.22   539.8  1126.3   559.8 1133.48   589.7 1143.02   619.7 1153.86
   649.7 1164.23   669.7 1171.96   679.7 1176.37   689.7 1181.38   699.7 1186.14
#Mann= 3 , 0 , 0
       0      .1       0   419.8    .045       0   441.3      .1       0
Bank Sta=419.8,441.3
XS Rating Curve= 0 ,0
Exp/Cntr=0.3,0.1

Type RM Length L Ch R = 1 ,8604.7  ,476.8,483.1,488.8
XS GIS Cut Line= 2
     1840395.571      374749.431     1840461.024        375348.8
#Sta/Elev= 30
       0 1091.67    39.5 1088.34    49.4 1087.68    79.1 1086.86    98.8 1086.52
   247.1 1085.92     257 1085.61   276.8  1084.5   296.5 1083.83   365.7 1082.87
   385.5 1082.91   395.4 1082.41   397.7 1082.06   405.2 1080.92   415.1 1081.11
     425 1082.06   434.9 1081.99   444.8 1083.88   454.7 1087.67   464.6 1092.19
   484.3  1101.5   494.2 1106.94   504.1  1113.5     514 1119.06   533.7 1128.28
   543.6 1132.07   553.5 1135.39   573.3 1144.13     593 1151.29   602.9  1154.7
#Mann= 3 , 0 , 0
       0      .1       0   397.7    .045       0     425      .1       0
Bank Sta=397.7,425
XS Rating Curve= 0 ,0
Exp/Cntr=0.3,0.1

Type RM Length L Ch R = 1 ,8121.6  ,319.2,330.8,342.1
XS GIS Cut Line= 2
      1840086.58      374689.693     1840008.205      375362.306
#Sta/Elev= 30
       0 1097.39    29.9  1095.8    49.8 1093.54    59.8  1091.8    69.7 1090.54
    79.7 1090.21    89.6  1089.3    99.6 1087.68   129.5 1081.15   139.4 1079.43
   149.4  1078.3   199.2 1078.72     229 1078.54   258.9  1077.2   278.8 1075.05
   288.8 1073.96   298.8 1074.72   308.7 1077.01   338.6 1078.32   368.5 1076.99
   398.3 1076.92     478 1078.42   507.9  1080.1   527.8 1081.91   547.7 1083.33
   567.6 1084.25   587.5 1084.49   597.5 1084.91   627.4 1087.58   677.2 1090.21
#Mann= 3 , 0 , 0
       0      .1       0   278.8    .045       0   298.8      .1       0
Bank Sta=278.8,298.8
XS Rating Curve= 0 ,0
Exp/Cntr=0.3,0.1

Type RM Length L Ch R = 1 ,7790.8  ,253.1,239.6,226.5
XS GIS Cut Line= 3
     1839972.081      374540.449     1839718.609      374901.561
     1839701.644      375353.571
#Sta/Elev= 30
       0 1114.34    19.6 1109.48    78.4 1096.38   127.5 1090.42   147.1 1088.71
   156.9 1088.15   225.5 1086.45   235.3 1085.53   245.1 1082.84   264.7 1075.46
   274.5 1072.78   284.3 1071.82   343.2 1070.62   362.8 1069.24   372.6 1070.54
   382.4 1071.53   421.6 1072.78   519.9 1073.65   637.9 1074.02   677.2 1074.59
   706.7 1075.78   736.2 1078.09   755.8 1078.69   775.5  1080.2   785.4 1081.39
     805 1086.38   834.5 1092.65   844.4 1095.29   873.8 1104.71   893.5 1109.96
#Mann= 3 , 0 , 0
       0      .1       0   343.2    .045       0   372.6      .1       0
Bank Sta=343.2,372.6
XS Rating Curve= 0 ,0
Exp/Cntr=0.3,0.1

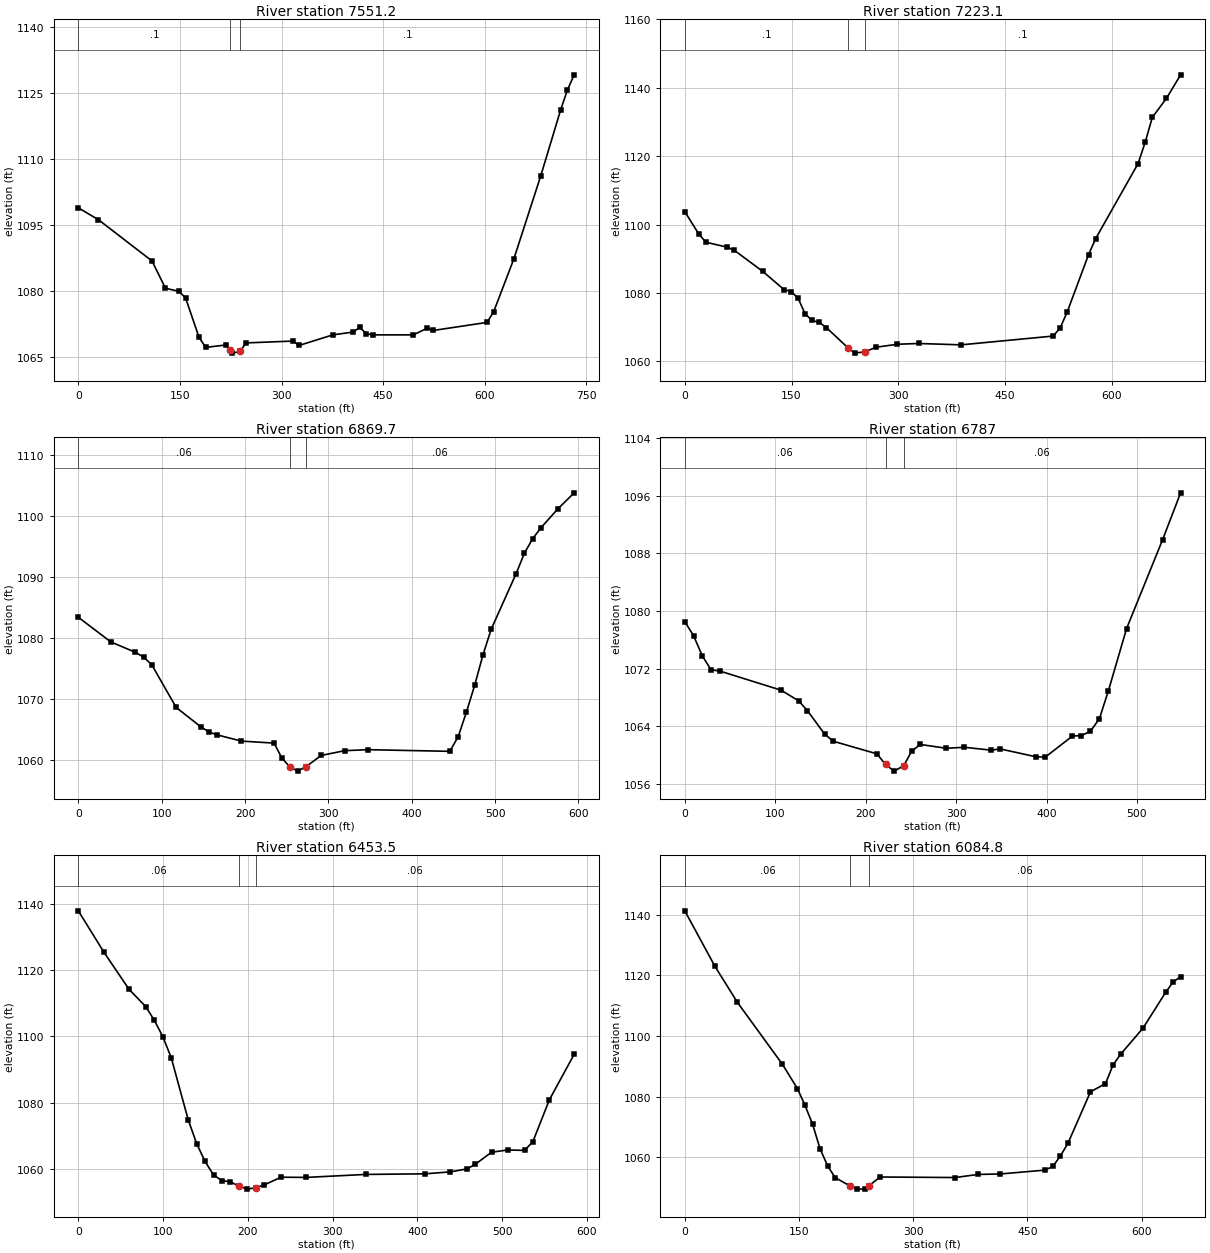
Type RM Length L Ch R = 1 ,7551.2  ,346,328.1,332.9
XS GIS Cut Line= 2
     1839561.224      374538.289     1839537.237      375269.901
#Sta/Elev= 30
       0 1098.82    29.7 1096.12   108.8 1086.74   128.6 1080.55   148.4 1079.84
   158.3 1078.37   178.1 1069.42     188  1067.1   217.6 1067.65   224.2 1066.42
   227.5  1065.8   239.2 1066.22   247.3 1068.12   316.5 1068.54   326.4 1067.57
   375.9 1069.96   405.6 1070.58   415.5 1071.65   425.4 1070.19   435.2 1069.95
   494.6 1069.95   514.4 1071.42   524.3 1070.96   603.4 1072.78   613.3 1075.26
     643 1087.23   682.6 1106.05   712.2 1121.15   722.1 1125.63     732 1129.05
#Mann= 3 , 0 , 0
       0      .1       0   224.2    .045       0   239.2      .1       0
#XS Ineff= 2 , 0
                          415.94         1071.52
Permanent Ineff=
       F       F
Bank Sta=224.2,239.2
XS Rating Curve= 0 ,0
Exp/Cntr=0.3,0.1

Type RM Length L Ch R = 1 ,7223.1  ,332,353.4,363.9
XS GIS Cut Line= 2
     1839335.587      374470.444     1839221.004      375157.944
#Sta/Elev= 30
       0 1103.81    19.9 1097.16    29.9 1094.85    59.7  1093.4    69.7 1092.48
   109.5 1086.34   139.4 1081.03   149.4 1080.44   159.3 1078.48   169.3 1073.83
   179.2 1071.97   189.2  1071.4   199.1 1069.87     229 1064.06     239 1062.43
   253.1 1062.82   268.8 1064.15   298.7 1065.02   328.6 1065.25   388.3 1064.85
   517.8 1067.42   527.7 1069.79   537.7 1074.54   567.5 1091.19   577.5 1095.89
   637.2 1117.85   647.2 1124.11   657.2 1131.36   677.1 1136.93     697  1143.8
#Mann= 3 , 0 , 0
       0      .1       0     229    .045       0   253.1      .1       0
Bank Sta=229,253.1
XS Rating Curve= 0 ,0
Exp/Cntr=0.3,0.1

Type RM Length L Ch R = 1 ,6869.7  ,97.7,82.7,77.8
XS GIS Cut Line= 4
     1839116.718      374598.435     1838985.097      374792.874
     1838935.157      374925.069     1838860.399      375130.654
#Sta/Elev= 30
       0 1083.37    39.1 1079.31    68.5 1077.62    78.3 1076.82      88  1075.6
   117.4 1068.56   146.8  1065.4   156.5 1064.56   166.3 1064.07   195.7 1063.04
   234.8 1062.71   244.2 1060.27   253.6 1058.81   263.1 1058.11   273.3 1058.85
   291.3 1060.68   319.6 1061.47   347.8 1061.63   445.7 1061.36   455.7 1063.74
   465.6 1067.79   475.6 1072.24   485.5  1077.2   495.4 1081.42   525.3 1090.54
   535.2 1093.89   545.2 1096.28   555.1 1098.07     575 1101.12   594.9  1103.8
#Mann= 3 , 0 , 0
       0     .06       0   253.6    .045       0   273.3     .06       0
Bank Sta=253.6,273.3
XS Rating Curve= 0 ,0
Exp/Cntr=0.3,0.1

Type RM Length L Ch R = 1 ,6787    ,348.4,333.5,319.2
XS GIS Cut Line= 4
     1839006.655      374632.208     1838925.256      374752.456
     1838870.945      374896.221     1838785.697      375130.654
#Sta/Elev= 30
       0 1078.54     9.7 1076.56    19.4 1073.77      29 1071.84    38.7 1071.67
   106.5 1069.01   125.8 1067.54   135.5 1066.19   154.8 1062.89   164.4 1061.92
   212.4 1060.18     222  1058.7   231.6 1057.78   242.2 1058.55   250.9 1060.56
   260.5 1061.48   289.3 1060.95   308.9 1061.09   338.8 1060.69   348.8 1060.86
   388.7 1059.76   398.7 1059.73   428.6 1062.64   438.6 1062.72   448.6 1063.31
   458.5 1065.06   468.5 1068.96   488.5 1077.55   528.4 1089.91   548.3  1096.4
#Mann= 3 , 0 , 0
       0     .06       0     222    .045       0   242.2     .06       0
Bank Sta=222,242.2
XS Rating Curve= 0 ,0
Exp/Cntr=0.3,0.1

Type RM Length L Ch R = 1 ,6453.5  ,380.8,368.7,356.4
XS GIS Cut Line= 4
     1838511.078      374626.777     1838586.999      374905.691
     1838696.037       374993.43     1838761.213      375135.195
#Sta/Elev= 30
       0 1137.84    29.9 1125.49    59.8 1114.21    79.7 1108.93    89.7 1104.84
    99.7 1099.93   109.6 1093.61   129.6 1074.93   139.6 1067.71   149.5 1062.36
   159.5 1058.28   169.4 1056.58   179.4  1056.2   189.9 1054.86   199.4 1054.01
   209.3 1054.45   219.3 1055.28   239.2  1057.6   269.1 1057.54     339 1058.44
     409 1058.62   438.8 1059.21   458.3 1060.08     468 1061.43   487.5 1065.12
     507 1065.82   526.5 1065.67   536.3 1068.32   555.8 1080.94     585 1094.62
#Mann= 3 , 0 , 0
       0     .06       0   189.9    .045       0   209.3     .06       0
Bank Sta=189.9,209.3
XS Rating Curve= 0 ,0
Exp/Cntr=0.3,0.1

Type RM Length L Ch R = 1 ,6084.8  ,343.8,339.2,334.6
XS GIS Cut Line= 2
     1838139.955      374874.421     1838600.593      375334.857
#Sta/Elev= 30
       0 1141.26    39.5 1123.01    69.1 1111.09   128.3 1090.65     148 1082.63
   157.9 1077.15   167.8 1070.96   177.6 1062.88   187.5 1057.24   197.4 1053.36
   217.1 1050.56   226.8 1049.55   236.8 1049.53   241.8 1050.65   256.6 1053.53
   355.2 1053.35   384.9 1054.37   414.5 1054.53   473.7 1055.81   483.5 1057.06
   493.4 1060.45   503.3 1064.64   532.9 1081.61   552.6  1084.3   562.5 1090.43
   572.4 1093.96     602 1102.63   631.6 1114.37   641.4 1117.81   651.3 1119.55
#Mann= 3 , 0 , 0
       0     .06       0   217.1    .045       0   241.8     .06       0
Bank Sta=217.1,241.8
XS Rating Curve= 0 ,0
Exp/Cntr=0.3,0.1

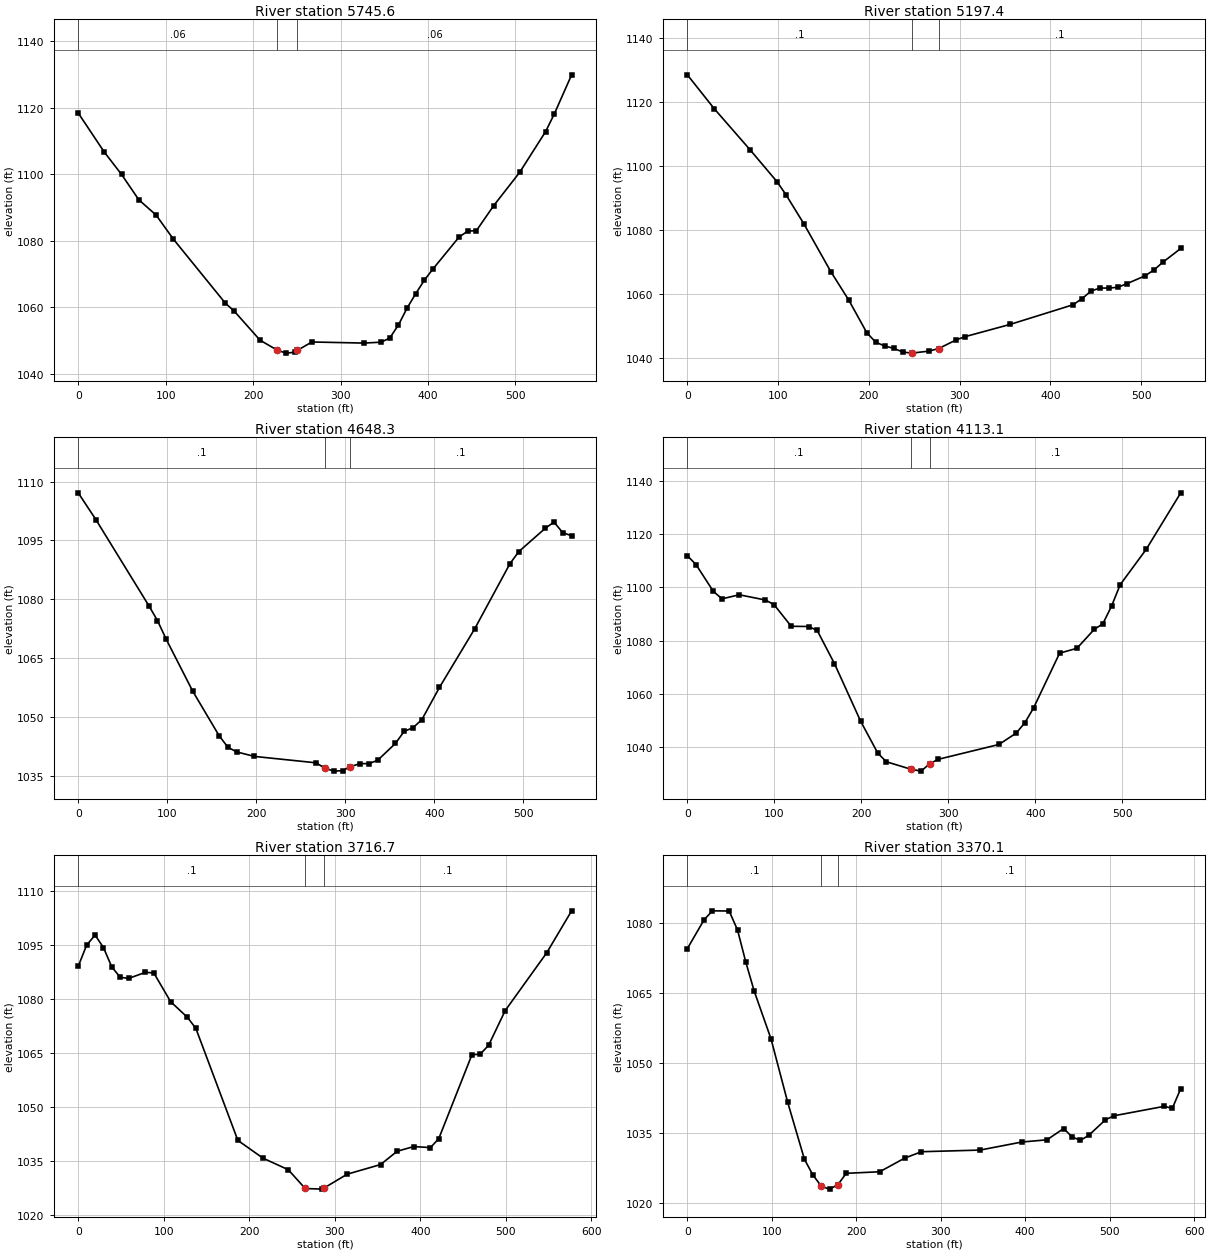
Type RM Length L Ch R = 1 ,5745.6  ,550.4,548.2,545
XS GIS Cut Line= 2
     1837985.591      375205.861     1838457.474       375515.11
#Sta/Elev= 30
       0 1118.36    29.7 1106.66    49.5 1099.91    69.3 1092.28    89.1 1087.67
   108.9 1080.42   168.3 1061.19   178.2 1058.87   207.9 1050.08   227.6 1047.08
   237.6 1046.19   247.4 1046.44   250.6 1047.02   267.2 1049.54   326.6 1049.21
   346.4 1049.48   356.3 1050.73   366.2 1054.68   376.1 1059.74     386 1064.09
   395.9 1068.15   405.8 1071.53   435.5 1081.07   445.4 1082.86   455.3 1082.99
   475.1 1090.52   504.8 1100.52   534.5 1112.79   544.4 1118.08   564.2 1129.83
#Mann= 3 , 0 , 0
       0     .06       0   227.6    .045       0   250.6     .06       0
Bank Sta=227.6,250.6
XS Rating Curve= 0 ,0
Exp/Cntr=0.3,0.1

Type RM Length L Ch R = 1 ,5197.4  ,543.7,549.1,554.5
XS GIS Cut Line= 2
     1837757.634      375697.329     1838250.291      375927.617
#Sta/Elev= 30
       0 1128.48    29.7 1117.87    69.2 1105.02    98.9 1095.04   108.8 1090.95
   128.5 1081.86   158.2 1066.91     178    1058   197.8 1047.84   207.6 1044.88
   217.5 1043.68   227.4 1042.96   237.3 1041.82   247.2 1041.46     266 1042.08
   276.9 1042.88   296.6 1045.64   306.5 1046.64     356 1050.46   425.2 1056.59
   435.1 1058.52     445 1060.88   454.8 1061.82   464.7 1061.79   474.6 1062.07
   484.5 1063.18   504.3 1065.61   514.2 1067.44     524 1069.86   543.8 1074.19
#Mann= 3 , 0 , 0
       0      .1       0   247.2    .045       0   276.9      .1       0
Bank Sta=247.2,276.9
XS Rating Curve= 0 ,0
Exp/Cntr=0.3,0.1

Type RM Length L Ch R = 1 ,4648.3  ,535.5,535.2,532.7
XS GIS Cut Line= 2
     1837532.754      376068.148     1837942.765      376440.818
#Sta/Elev= 30
       0 1107.14    19.8 1100.33    79.2 1078.41      89 1074.57    98.9 1069.77
   128.6 1056.57   158.3  1045.2   168.2 1042.25   178.1 1041.08   197.9 1039.94
   267.1 1038.31     277 1036.94   286.9 1036.19   296.8  1036.3   305.4 1037.32
   316.6 1038.11   326.5 1038.09   336.4 1038.98   356.2 1043.24   366.1 1046.34
     376 1047.26   385.9 1049.31   405.7 1057.54   445.2 1072.45   484.8 1089.06
   494.7 1092.14   524.4 1098.08   534.3 1099.68   544.2 1096.97   554.1  1096.2
#Mann= 3 , 0 , 0
       0      .1       0     277    .045       0   305.4      .1       0
Bank Sta=277,305.4
XS Rating Curve= 0 ,0
Exp/Cntr=0.3,0.1

Type RM Length L Ch R = 1 ,4113.1  ,396.7,396.4,385.8
XS GIS Cut Line= 2
     1837229.473      376415.755      1837645.99      376800.545
#Sta/Elev= 30
       0 1111.92      10 1108.57    29.8 1098.54    39.8 1095.69    59.7 1097.22
    89.5 1095.26    99.5 1093.55   119.4 1085.36   139.3 1085.28   149.2 1083.81
   169.1 1071.29     199 1049.74   218.9  1037.6   228.8 1034.37   257.1 1031.56
   268.6 1030.86   278.6 1033.66   288.5 1035.32   358.1 1040.89     378 1045.19
     388 1049.14   397.9 1054.65   427.8 1075.25   447.7 1077.08   467.6  1084.2
   477.5 1086.31   487.5 1092.97   497.4 1101.01   527.3 1114.31     567 1135.58
#Mann= 3 , 0 , 0
       0      .1       0   257.1    .045       0   278.6      .1       0
Bank Sta=257.1,278.6
XS Rating Curve= 0 ,0
Exp/Cntr=0.3,0.1

Type RM Length L Ch R = 1 ,3716.7  ,346.3,346.5,352.1
XS GIS Cut Line= 3
     1836962.321      376728.195     1837248.743      376900.275
     1837458.476      377022.816
#Sta/Elev= 30
       0 1089.12     9.8    1095    19.7 1097.82    29.5 1094.36    39.3 1088.95
    49.1 1086.09      59 1085.78    78.6 1087.46    88.4  1087.3   108.1  1079.3
   127.8 1074.94   137.6 1071.87   186.7 1040.75   216.2  1035.8   245.7  1032.6
   265.4 1027.39     285 1027.21   287.8 1027.56   314.5 1031.36   353.6 1034.04
     373 1037.74   392.4 1039.04   411.9 1038.75   421.6 1041.22   460.4 1064.55
   470.2 1064.73   479.9 1067.18   499.3 1076.82   547.9  1092.9     577 1104.56
#Mann= 3 , 0 , 0
       0      .1       0   265.4    .045       0   287.8      .1       0
Bank Sta=265.4,287.8
XS Rating Curve= 0 ,0
Exp/Cntr=0.3,0.1

Type RM Length L Ch R = 1 ,3370.1  ,416.8,421.5,426.2
XS GIS Cut Line= 2
      1836794.27      376914.565     1837204.477      377330.388
#Sta/Elev= 30
       0 1074.59    19.8 1080.78    29.7  1082.7    49.5 1082.66    59.4  1078.6
    69.3 1071.65    79.2 1065.46      99 1055.28   118.8 1041.65   138.6 1029.45
   148.5 1026.11   158.8 1023.63   168.3 1023.04   178.2 1023.98   188.1 1026.43
   227.7 1026.76   257.4  1029.7   277.2 1031.06   346.5 1031.41     396 1033.14
   425.7 1033.61   445.5 1036.03   455.4 1034.25   465.3 1033.49   475.2 1034.57
     495 1037.91   504.9 1038.76   564.3 1040.78   574.2 1040.38   584.1 1044.61
#Mann= 3 , 0 , 0
       0      .1       0   158.8    .045       0   178.2      .1       0
Bank Sta=158.8,178.2
XS Rating Curve= 0 ,0
Exp/Cntr=0.3,0.1

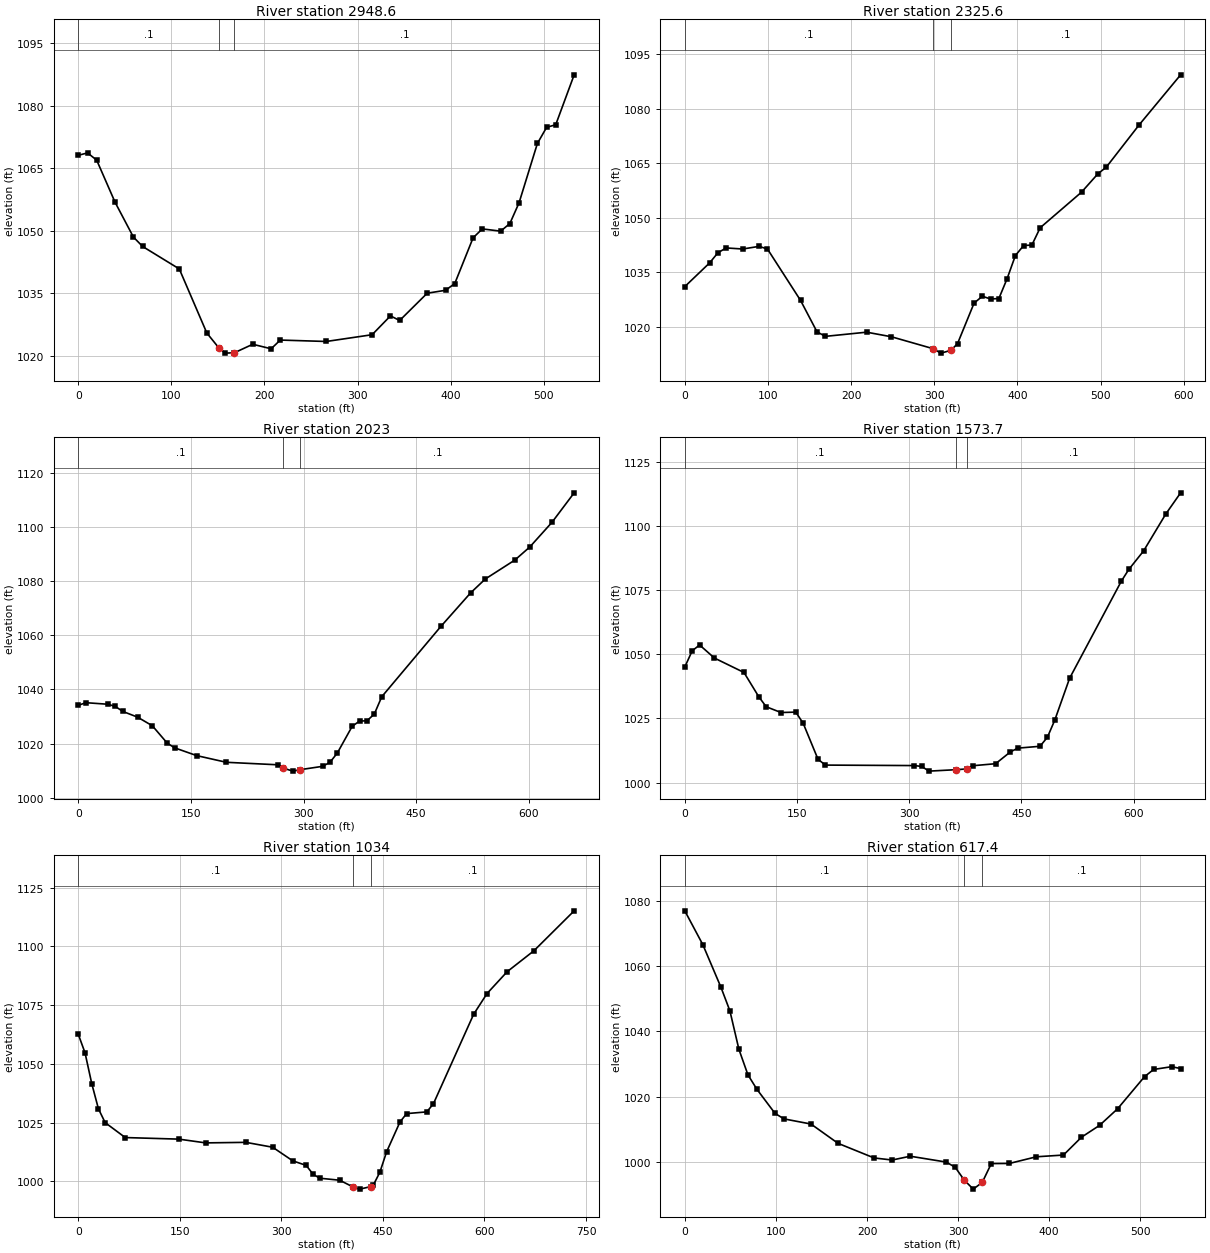
Type RM Length L Ch R = 1 ,2948.6  ,608.3,623.1,628.7
XS GIS Cut Line= 2
     1836505.202      377173.066     1836797.138      377618.724
#Sta/Elev= 30
       0 1068.09     9.9 1068.66    19.7 1066.94    39.5 1056.83    59.2  1048.5
    69.1 1046.25   108.5 1040.87   138.1 1025.52   150.8 1022.02   157.9 1020.71
   167.7  1020.8   187.4 1022.83   207.2 1021.75     217 1023.84   266.4  1023.5
   315.7 1025.12   335.4 1029.63   345.3 1028.53   374.9 1035.06   394.6 1035.76
   404.5 1037.37   424.2 1048.33   434.1 1050.46   453.8 1049.92   463.7 1051.74
   473.6 1056.72   493.3 1070.93   503.2 1074.78     513 1075.41   532.8 1087.36
#Mann= 3 , 0 , 0
       0      .1       0   150.8    .045       0   167.7      .1       0
Bank Sta=150.8,167.7
XS Rating Curve= 0 ,0
Exp/Cntr=0.3,0.1

Type RM Length L Ch R = 1 ,2325.6  ,302.5,302.5,302.6
XS GIS Cut Line= 2
     1836062.724      377296.013     1836195.971      377877.276
#Sta/Elev= 30
       0 1031.08    29.8 1037.59    39.8 1040.38    49.7 1041.72    69.6 1041.42
    89.4 1042.15    99.4 1041.42   139.2 1027.29     159 1018.65     169  1017.4
   218.7 1018.55   248.5 1017.29   298.2 1014.04   308.1 1012.79   320.1 1013.56
     328  1015.4   347.9 1026.54   357.8 1028.43   367.7 1027.68   377.7  1027.8
   387.6 1033.25   397.6 1039.63   407.5 1042.38   417.4 1042.51   427.4 1047.27
   477.1 1057.05     497 1062.15   506.9 1063.93   546.6 1075.61   596.3 1089.32
#Mann= 3 , 0 , 0
       0      .1       0   298.2    .045       0   320.1      .1       0
#XS Ineff= 2 , 0
          214.17 1018.37
Permanent Ineff=
       F       F
Bank Sta=298.2,320.1
XS Rating Curve= 0 ,0
Exp/Cntr=0.3,0.1

Type RM Length L Ch R = 1 ,2023    ,438.7,449.4,460
XS GIS Cut Line= 2
     1835776.071      377393.423     1835921.319      378037.764
#Sta/Elev= 30
       0 1034.13     9.9 1035.12    39.4 1034.54    49.3 1033.73    59.2 1031.88
    78.9 1029.77    98.6 1026.57   118.3 1020.18   128.2 1018.41   157.7 1015.52
   197.2 1013.05   266.2 1012.12   272.8 1010.89   285.9 1009.78   295.8 1010.33
   325.3 1011.55   335.2 1013.04     345 1016.48   364.8 1026.37   374.6 1028.32
   384.5 1028.41   394.3 1030.92   404.2 1037.32   483.1  1063.4   522.5 1075.75
   542.2 1080.92   581.6 1087.94   601.4 1092.76   630.9 1101.87   660.5 1112.81
#Mann= 3 , 0 , 0
       0      .1       0   272.8    .045       0   295.8      .1       0
Bank Sta=272.8,295.8
XS Rating Curve= 0 ,0
Exp/Cntr=0.3,0.1

Type RM Length L Ch R = 1 ,1573.7  ,538.5,539.7,540
XS GIS Cut Line= 2
     1835495.722      377351.022     1835317.056      377989.259
#Sta/Elev= 30
       0 1045.04     9.9 1051.35    19.8 1053.61    39.6 1048.52    79.1 1042.91
    98.9 1033.46   108.8 1029.57   128.6 1027.32   148.4 1027.48   158.3 1023.09
   178.1 1009.11     188 1006.86   306.7 1006.67   316.6 1006.35   326.4 1004.51
     362 1005.06     377 1005.36   385.8 1006.63   415.5  1007.4   435.2 1011.99
   445.2 1013.46   474.8 1014.18   484.7 1017.68   494.6 1024.38   514.4 1040.66
   583.6 1078.48   593.5    1083   613.3 1090.22     643  1104.6   662.8 1112.83
#Mann= 3 , 0 , 0
       0      .1       0     362    .045       0     377      .1       0
Bank Sta=362,377
XS Rating Curve= 0 ,0
Exp/Cntr=0.3,0.1

Type RM Length L Ch R = 1 ,1034    ,425.4,416.6,407.6
XS GIS Cut Line= 2
     1835015.456      377128.583     1834817.986      377833.993
#Sta/Elev= 30
       0 1062.55     9.9 1054.71    19.8 1041.64    29.7  1030.9    39.6 1025.04
    69.3 1018.68   148.5 1018.01   188.1 1016.41   247.5 1016.64   287.1 1014.56
   316.8 1008.77   336.6 1006.84   346.5 1003.18   356.4 1001.39   386.1 1000.53
   405.9  997.65   415.8  996.74     432  997.81   435.6  998.35   445.5 1003.95
   455.4  1012.6   475.2 1025.32     485 1028.87   514.8  1029.6   524.6 1033.07
     584 1071.12   603.8 1079.95   633.5 1089.23   673.1 1098.15   732.5 1115.13
#Mann= 3 , 0 , 0
       0      .1       0   405.9    .045       0     432      .1       0
Bank Sta=405.9,432
XS Rating Curve= 0 ,0
Exp/Cntr=0.3,0.1

Type RM Length L Ch R = 1 ,617.4   ,413.8,413.8,413.6
XS GIS Cut Line= 2
     1834467.945      377212.862      1834530.97      377753.434
#Sta/Elev= 30
       0 1076.85    19.8  1066.5    39.6 1053.53    49.5 1046.27    59.4 1034.49
    69.3  1026.7    79.2 1022.26      99 1014.93   108.8 1013.24   138.5 1011.66
   168.2 1005.76   207.8 1001.29   227.6 1000.66   247.4 1001.82     287 1000.03
   296.8  998.43   306.8  994.49   316.6  991.76   326.5  993.83   336.4  999.57
   356.2  999.61   385.9 1001.65   415.6 1002.18   435.4 1007.64   455.2 1011.25
     475 1016.32   504.6 1026.15   514.6 1028.35   534.3 1029.19   544.2 1028.63
#Mann= 3 , 0 , 0
       0      .1       0   306.8    .045       0   326.5      .1       0
Bank Sta=306.8,326.5
XS Rating Curve= 0 ,0
Exp/Cntr=0.3,0.1

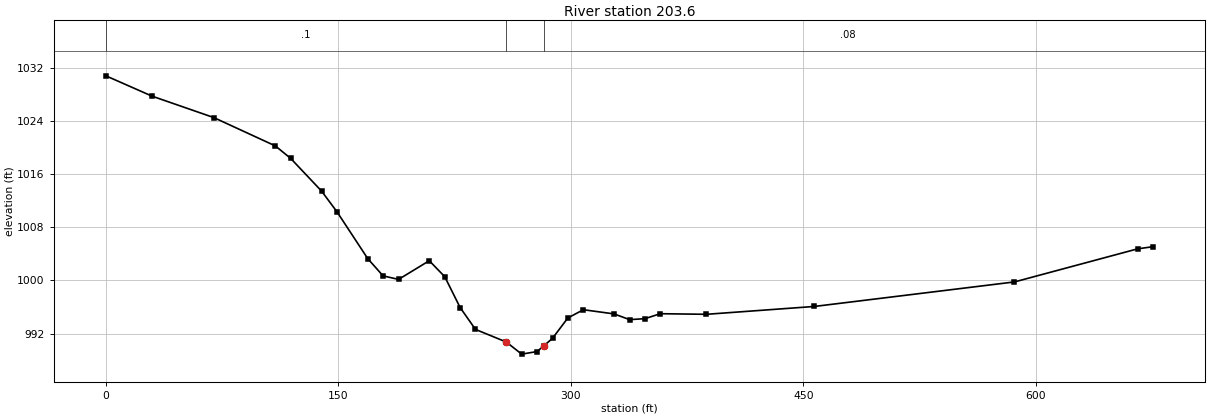
Type RM Length L Ch R = 1 ,203.6   ,222.6,203.6,184.6
XS GIS Cut Line= 2
     1834062.526      377280.885     1834140.753       377951.85
#Sta/Elev= 30
       0 1030.76    29.8  1027.7    69.5 1024.49   109.3 1020.22   119.2 1018.34
   139.1 1013.43     149 1010.33   168.9 1003.27   178.8 1000.67   188.8 1000.14
   208.6 1002.95   218.6 1000.54   228.5  995.91   238.4  992.62   258.3  990.72
   268.2   988.9   278.2  989.29   282.3  990.11   288.1  991.28     298  994.34
     308  995.58   327.8  994.95   337.8  994.09   347.7  994.23   357.6  994.98
   387.4  994.89     457  996.07   586.1  999.76   665.6 1004.74   675.5 1005.06
#Mann= 3 , 0 , 0
       0      .1       0   258.3    .045       0   282.3     .08       0
#XS Ineff= 2 , 0
                          310.63          995.46
Permanent Ineff=
       F       F
Bank Sta=258.3,282.3
XS Rating Curve= 0 ,0
Exp/Cntr=0.3,0.1

Chan Stop Cuts=-1
Use User Specified Reach Order=0
Composite Channel Slope=5